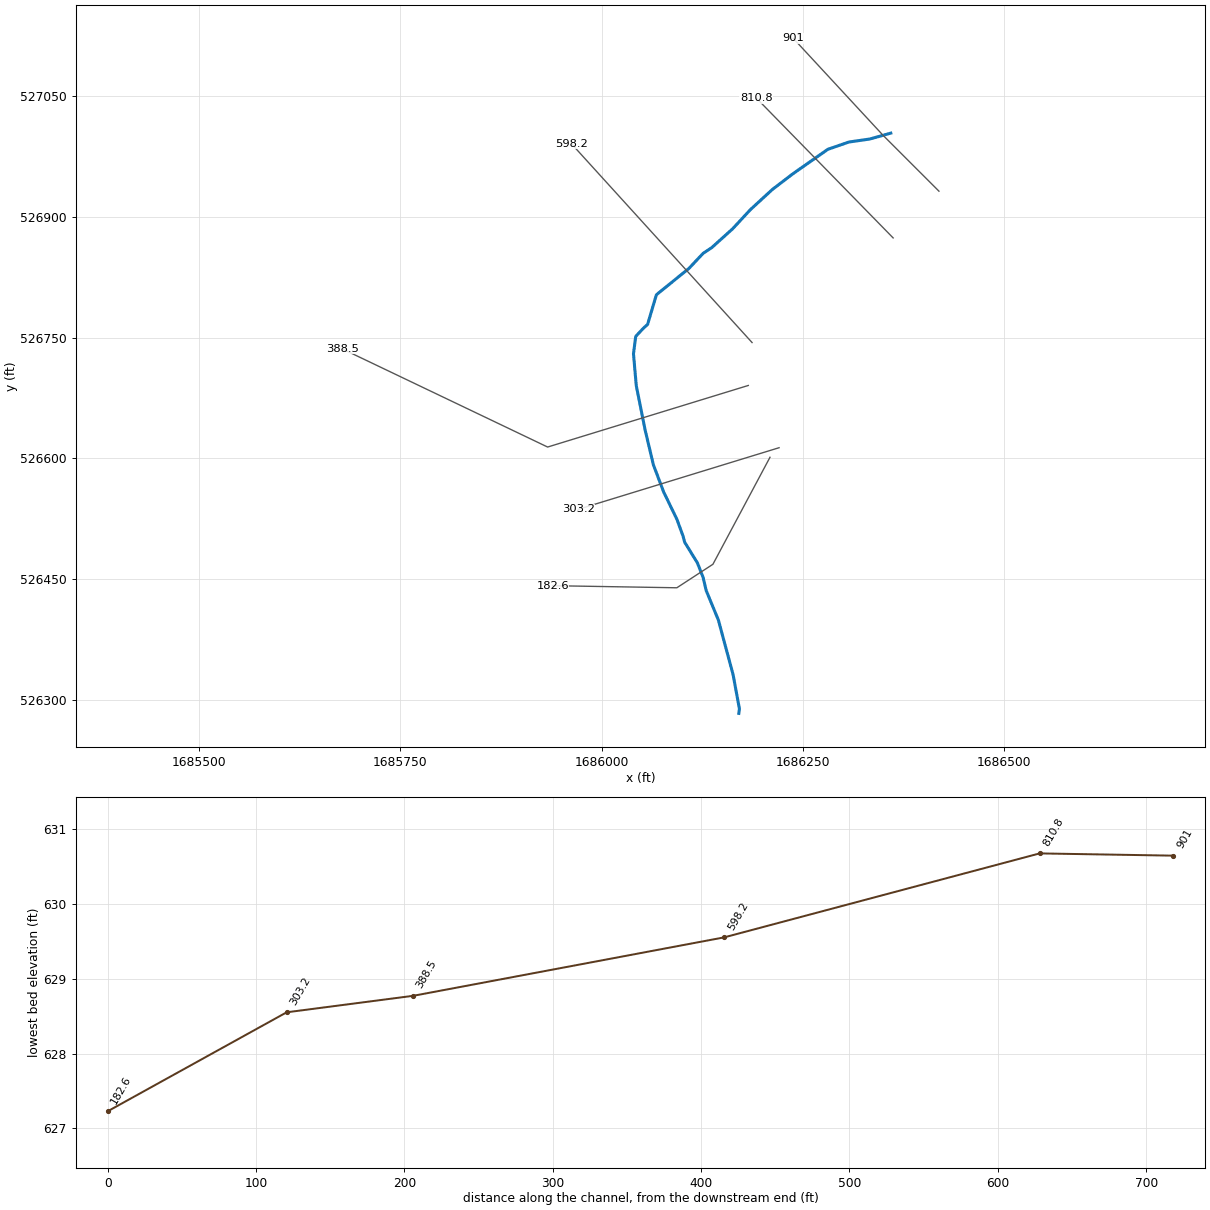
--- NP10.prj (project) ---

Proj Title=NP10
Current Plan=p01
Default Exp/Contr=0,0
English Units
Geom File=g01
Flow File=f01
Plan File=p01
BEGIN DESCRIPTION:
AMEC Environment & Infrastructure, 2013
Projection: NAD 1983 State Plane West Virginia South FIPS 4702 (US Feet)
Vertical Datum: NAVD 1988
END DESCRIPTION:
DSS Export Rating Curves= 0
DSS Export Rating Curve Sorted= 0
DSS Export Volume Flow Curves= 0
DXF OffsetX= 0
DXF OffsetY= 0
DXF ScaleX= 0
DXF ScaleY= 0

--- NP10.p01 (plan) ---

Plan Title=Floodplain
Program Version=4.00
Geom File=g01
Flow File=f01
K Sum by GR=0
Std Step Tol=0.01
Critical Tol=0.01
Num of Std Step Trials=20
Max Error Tol=0.3
Flow Tol Ratio=0.001
Split Flow NTrial=30
Split Flow Tol=0.02
Split Flow Ratio=0.02
Log Output Level=0
Friction Slope Method=1
Unsteady Friction Slope Method=2
Unsteady Bridges Friction Slope Method=1
Global Log Level=0
CheckData=False
Run HTab=0
Run UNet=0
Run PostProcess=0
UNET Theta=0
UNET Theta Warmup=0
UNET ZTol=0
UNET ZSATol=0
UNET MxIter=0
UNET MaxInSteps=0
UNET DtIC=0
UNET DtMin=0
UNET MaxCRTS=0
UNET WFStab=0
UNET SFStab=0
UNET WFX=0
UNET SFX=0
UNET DSS MLevel=0
UNET DZMax Abort=0
UNET Convert EG Bridges=0
UNET Use Existing IB Tables=0
UNET Froude Limit=0
UNET Froude Power=0
Write IC File=0
Echo Input=False
Echo Output=False
Write Detailed=0

--- NP10.f01 (steady flow) ---

Flow Title=USGS Regress. Eqn. (2010) - Western-Plateaus
Program Version=4.00
Number of Profiles=1
Profile Names=P100yr
River Rch & RM=NP10,Main      ,901
    1053
River Rch & RM=NP10,Main      ,388.5
    1066
River Rch & RM=NP10,Main      ,182.6
    1068
Boundary for River Rch & Prof#=NP10,Main      ,1
Up Type=0
Dn Type=3
Dn Slope=0.005755

--- NP10.g01 (geometry) ---

Geom Title=USGS 3m DEM
Program Version=4.10

River Reach=NP10            ,Main
Reach XY= 30
      1686359.11       527003.92     1686333.067      526996.591
     1686307.107      526992.851     1686280.976       526983.82
     1686237.396       526953.31     1686212.152      526934.003
     1686184.876      526908.966     1686162.597       526884.97
      1686136.89      526861.831     1686126.175      526854.687
     1686108.526      526835.966     1686068.133      526803.263
     1686057.161      526766.347     1686052.174      526761.924
     1686042.452      526751.507     1686039.674      526729.979
     1686043.146      526690.396     1686054.171      526635.219
     1686064.377       526592.26     1686077.062      526558.603
     1686093.553      526524.596     1686101.283       526503.47
     1686103.246      526496.058     1686118.998      526470.465
     1686126.215      526452.125      1686129.94      526436.082
     1686145.029      526399.587     1686163.288      526331.892
     1686171.221      526289.007     1686170.431      526283.602

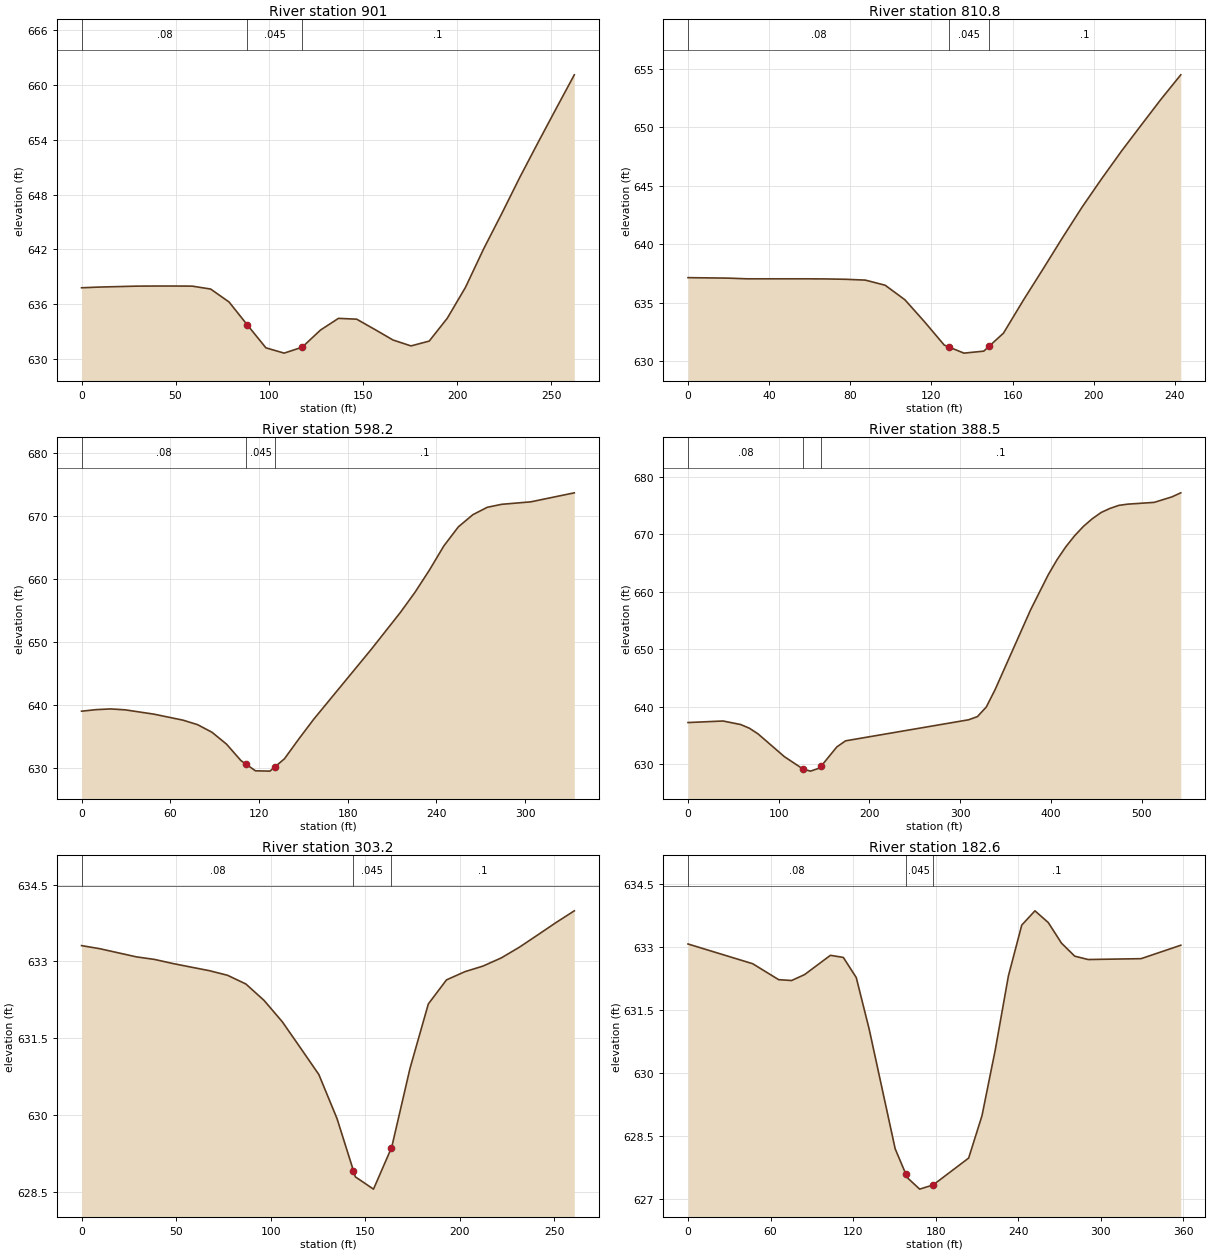
Type RM Length L Ch R = 1 ,901     ,91.5,90.2,89.1
XS GIS Cut Line= 3
     1686418.896      526931.839     1686349.484      527001.211
     1686238.025      527121.577
#Sta/Elev= 29
       0   637.8     9.8  637.88    19.6  637.93    29.4  637.98    39.2  637.99
    49.1  637.99    58.9  637.98    68.7  637.66    78.5  636.24    88.1  633.76
    98.1  631.22   107.8  630.64   108.1  630.66   117.4  631.29   127.1  633.16
   136.7  634.45   146.4  634.36     156  633.24   165.7  632.08   175.3  631.43
     185  631.96   194.6  634.46   204.3  637.85   213.9  642.04   223.6  645.93
   233.2   649.9   242.9  653.71   252.5  657.42   262.2  661.13
#Mann= 3 , 0 , 0
       0     .08       0    88.1    .045       0   117.4      .1       0
Bank Sta=88.1,117.4
XS Rating Curve= 0 ,0
Exp/Cntr=0.3,0.1

Type RM Length L Ch R = 1 ,810.8   ,213.3,212.6,211.4
XS GIS Cut Line= 2
     1686362.024      526873.805     1686192.176      527047.461
#Sta/Elev= 28
       0  637.13     9.7  637.11    19.4  637.09    29.2  637.03    38.9  637.03
    48.6  637.03    58.3  637.03      68  637.02    77.7  636.99    87.4  636.92
    97.2  636.48   106.9  635.24   116.6  633.35   126.3  631.36   128.5   631.2
     136  630.67   145.8  630.84   148.5  631.27   155.5  632.38   165.2  635.17
   174.9  637.84   184.6  640.55   194.3  643.18     204  645.62   213.8  647.99
   223.5  650.21   233.2  652.41   242.9  654.49
#Mann= 3 , 0 , 0
       0     .08       0   128.5    .045       0   148.5      .1       0
Bank Sta=128.5,148.5
XS Rating Curve= 0 ,0
Exp/Cntr=0.3,0.1

Type RM Length L Ch R = 1 ,598.2   ,180.5,209.7,238.6
XS GIS Cut Line= 2
     1686186.903       526743.93     1685962.875      526990.504
#Sta/Elev= 28
       0  639.06     9.8  639.31    19.6  639.42    29.4  639.28      49  638.59
    68.6  637.64    78.4  636.93    88.2  635.72      98  633.84   107.8  631.22
     111  630.69   117.6   629.6   127.4  629.55     131  630.27   137.2  631.51
     147  634.68   156.8  637.73     196  648.91   215.6  654.74   225.4  657.91
   235.2  661.45     245   665.3   254.8  668.32   264.6  670.25   274.4  671.43
   284.2   671.9   303.8  672.29   333.2  673.72
#Mann= 3 , 0 , 0
       0     .08       0     111    .045       0     131      .1       0
Bank Sta=111,131
XS Rating Curve= 0 ,0
Exp/Cntr=0.3,0.1

Type RM Length L Ch R = 1 ,388.5   ,85.4,85.3,85.4
XS GIS Cut Line= 3
     1686182.221      526690.667     1685933.105      526614.224
     1685678.155      526736.096
#Sta/Elev= 30
       0  637.22    38.6  637.49    57.9  636.88    67.6  636.24    77.2  635.25
   106.2  631.29   127.1   629.1   135.1  628.77   144.8  629.29   147.1   629.7
   164.1  632.99   173.7  634.04   309.3   637.7     319  638.25   328.8  639.92
   338.5  642.94   377.5  656.78     397   662.9   406.7  665.52   416.5   667.8
   426.2  669.72     436  671.36   445.7  672.68   455.5  673.77   465.2  674.47
     475     675   484.7  675.21   513.9  675.52   533.4  676.47   543.2  677.18
#Mann= 3 , 0 , 0
       0     .08       0   127.1    .045       0   147.1      .1       0
Bank Sta=127.1,147.1
XS Rating Curve= 0 ,0
Exp/Cntr=0.3,0.1

Type RM Length L Ch R = 1 ,303.2   ,108.4,120.6,127.6
XS GIS Cut Line= 2
      1686220.43      526613.393     1685971.314      526536.951
#Sta/Elev= 30
       0  633.31     9.6  633.25    19.3  633.17      29  633.09    38.6  633.04
    48.3  632.96    57.9  632.89    67.6  632.82    77.2  632.73    86.9  632.56
    96.5  632.24   106.2  631.82   115.8  631.31   125.5  630.79   135.1  629.93
   143.8  628.91   144.8  628.79   154.4  628.55   163.8  629.35   164.1  629.38
   173.7  630.91   183.4  632.17     193  632.64   202.7   632.8   212.3  632.91
     222  633.07   231.6  633.28   241.3  633.52   250.9  633.76   260.6  633.99
#Mann= 3 , 0 , 0
       0     .08       0   143.8    .045       0   163.8      .1       0
Bank Sta=143.8,163.8
XS Rating Curve= 0 ,0
Exp/Cntr=0.3,0.1

Type RM Length L Ch R = 1 ,182.6   ,197.9,182.6,171.2
XS GIS Cut Line= 4
     1686209.143      526601.541       1686138.3      526468.692
       1686093.5      526439.515     1685939.295       526442.11
#Sta/Elev= 26
       0  633.07      47   632.6    65.9  632.22    75.3   632.2    84.7  632.34
   103.5   632.8   112.9  632.75   122.3  632.27   131.7  631.04   150.6  628.19
   158.2   627.6   159.5   627.5   168.4  627.23   178.2  627.33     204  627.97
   213.7  628.98   223.3  630.54   232.9  632.31   242.6  633.52   252.2  633.86
   261.9  633.58   271.5  633.09   281.1  632.78   290.8   632.7   329.3  632.72
   358.2  633.04
#Mann= 3 , 0 , 0
       0     .08       0   158.2    .045       0   178.2      .1       0
Bank Sta=158.2,178.2
XS Rating Curve= 0 ,0
Exp/Cntr=0.3,0.1

Chan Stop Cuts=-1
Use User Specified Reach Order=0
Composite Channel Slope=5